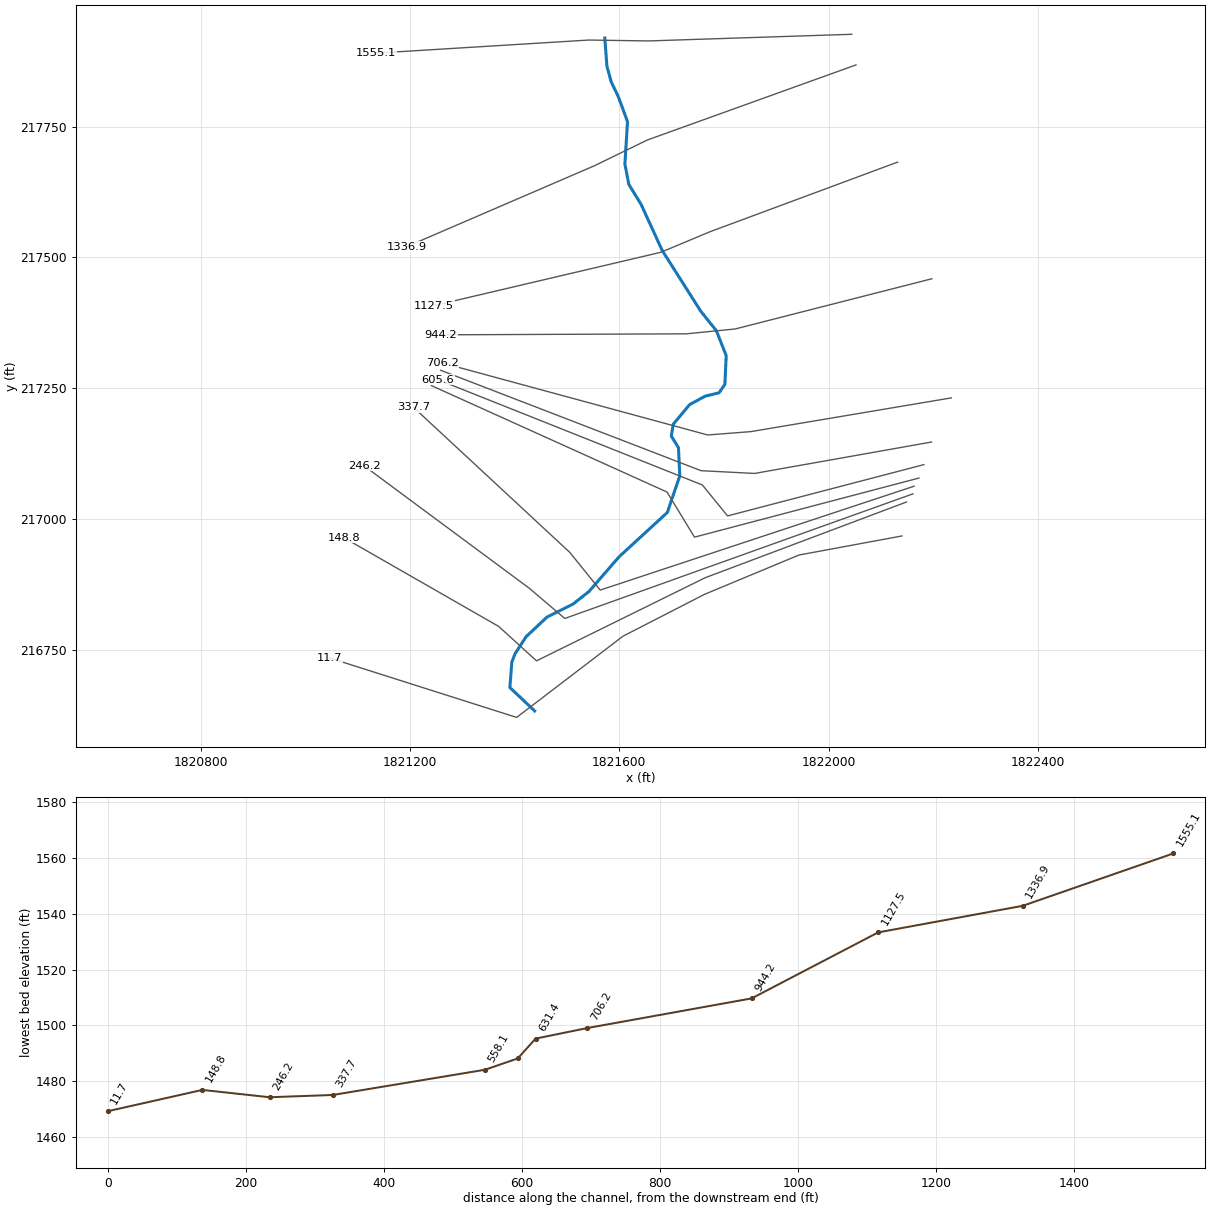
--- LthdFkBHFk.prj (project) ---

Proj Title=LthdFkBHFk
Current Plan=p01
Default Exp/Contr=0,0
English Units
Geom File=g01
Flow File=f01
Plan File=p01
BEGIN DESCRIPTION:
END DESCRIPTION:
DSS Export Rating Curves= 0
DSS Export Rating Curve Sorted= 0
DSS Export Volume Flow Curves= 0
DXF OffsetX= 0
DXF OffsetY= 0
DXF ScaleX= 0
DXF ScaleY= 0

--- LthdFkBHFk.p01 (plan) ---

Plan Title=Floodplain
Program Version=4.00
Geom File=g01
Flow File=f01
K Sum by GR=0
Std Step Tol=0.01
Critical Tol=0.01
Num of Std Step Trials=20
Max Error Tol=0.3
Flow Tol Ratio=0.001
Split Flow NTrial=30
Split Flow Tol=0.02
Split Flow Ratio=0.02
Log Output Level=0
Friction Slope Method=1
Unsteady Friction Slope Method=2
Unsteady Bridges Friction Slope Method=1
Global Log Level=0
CheckData=False
Run HTab=0
Run UNet=0
Run PostProcess=0
UNET Theta=0
UNET Theta Warmup=0
UNET ZTol=0
UNET ZSATol=0
UNET MxIter=0
UNET MaxInSteps=0
UNET DtIC=0
UNET DtMin=0
UNET MaxCRTS=0
UNET WFStab=0
UNET SFStab=0
UNET WFX=0
UNET SFX=0
UNET DSS MLevel=0
UNET DZMax Abort=0
UNET Convert EG Bridges=0
UNET Use Existing IB Tables=0
UNET Froude Limit=0
UNET Froude Power=0
Write IC File=0
Echo Input=False
Echo Output=False
Write Detailed=0

--- LthdFkBHFk.f01 (steady flow) ---

Flow Title=NFF Regression Equation
Program Version=4.00
Number of Profiles=1
Profile Names=P100yr
River Rch & RM=LthdFkBHFk,Main      ,1555.1
576.6331
River Rch & RM=LthdFkBHFk,Main      ,148.8
601.9351
Boundary for River Rch & Prof#=LthdFkBHFk,Main      ,1
Up Type=0
Dn Type=3
Dn Slope=0.017434

--- LthdFkBHFk.g01 (geometry) ---

Geom Title=USGS 10m DEM
Program Version=4.00

River Reach=LthdFkBHFk      ,Main
Reach XY= 30
     1821572.213      217919.232     1821576.264      217865.351
     1821584.387      217835.569     1821598.122      217806.849
     1821615.604      217759.399     1821610.609      217678.234
     1821618.101      217639.525     1821641.826      217600.816
     1821681.784      217513.408     1821755.456      217397.281
     1821785.425       217359.82     1821804.155       217312.37
     1821801.657      217257.428     1821790.419      217241.195
     1821764.197      217234.952     1821734.229      217218.719
     1821703.012      217181.259     1821699.266      217158.782
     1821713.001      217136.306     1821715.499      217082.613
     1821691.774      217012.686     1821599.371      216927.776
     1821541.932      216861.595     1821511.963       216837.87
     1821462.016      216812.897     1821422.058      216775.436
      1821400.83      216742.971     1821394.587      216726.738
     1821390.841      216678.039     1821438.202      216633.462

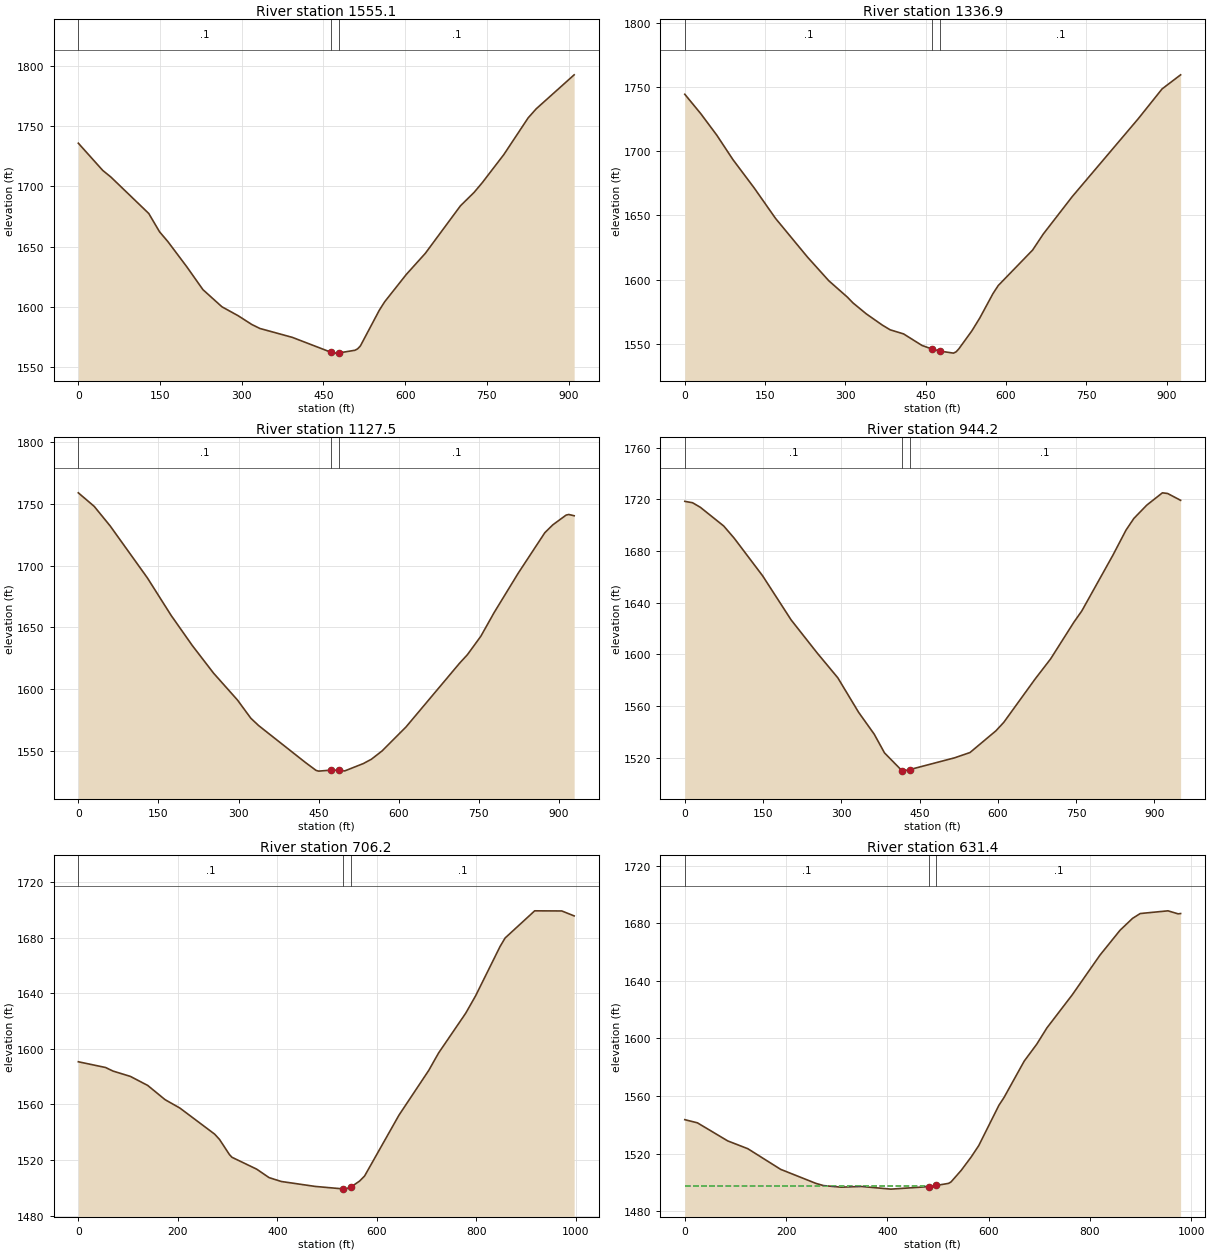
Type RM Length L Ch R = 1 ,1555.1  ,206.7,218.2,229.8
XS GIS Cut Line= 4
     1822044.162      217926.298     1821656.348      217913.601
     1821541.519      217915.286     1821134.864      217890.275
#Sta/Elev= 30
       0 1735.83    44.8 1713.24    59.7 1707.77   129.3 1677.49   149.2 1662.23
   164.2 1654.28     199 1633.33   228.8 1614.25   263.7 1600.03   293.5 1592.61
   318.4 1585.38   333.3 1582.06     393 1574.65   464.3 1562.24   472.9 1561.59
   479.3 1561.83   507.8 1563.96   512.8 1565.16   517.8 1567.53   552.6 1597.21
   562.5 1604.25   602.2 1626.93     637 1644.38   701.6 1683.88   726.4  1694.9
   741.4 1702.94   781.1 1726.32   825.8 1756.81   840.7 1764.39   910.3 1792.57
#Mann= 3 , 0 , 0
       0      .1       0   464.3    .045       0   479.3      .1       0
Bank Sta=464.3,479.3
XS Rating Curve= 0 ,0
Exp/Cntr=0.3,0.1

Type RM Length L Ch R = 1 ,1336.9  ,211.7,209.4,203.9
XS GIS Cut Line= 4
     1822052.216      217867.796     1821653.687      217724.375
      1821552.43      217675.123     1821194.249      217520.716
#Sta/Elev= 30
       0 1744.21    29.9 1729.08    59.8 1712.37    89.7 1693.51   129.6 1671.35
   169.4  1647.7   229.2 1617.54   269.1 1599.09     304 1586.28   313.9 1581.99
   338.8 1573.45   368.7 1564.71   383.7 1560.95   408.6  1557.8   443.1  1548.8
   462.2 1545.96   477.2 1544.36   501.9 1542.83   506.8 1543.84   511.7 1546.04
   536.2 1560.12     551 1570.12   575.6 1589.08   585.5  1595.4   649.7    1623
   669.5  1635.4   723.8 1664.62   847.2 1725.25   891.6 1748.39   926.2 1759.33
#Mann= 3 , 0 , 0
       0      .1       0   462.2    .045       0   477.2      .1       0
Bank Sta=462.2,477.2
XS Rating Curve= 0 ,0
Exp/Cntr=0.3,0.1

Type RM Length L Ch R = 1 ,1127.5  ,190.1,183.2,178.1
XS GIS Cut Line= 4
     1822131.619      217682.012     1821772.942      217548.911
     1821679.374      217509.769     1821246.458      217408.045
#Sta/Elev= 30
       0 1759.04    29.8 1748.02    59.6  1732.2   129.2 1690.13   173.9 1659.57
   213.6 1635.11   253.4 1612.72   298.1 1590.98     323 1576.26   337.9 1570.19
     426  1540.1   445.4 1533.87   450.2 1533.31   472.5 1534.09   487.5 1534.15
     499 1533.48     534 1539.48     549 1542.98     569 1549.71   613.9 1569.21
   713.8  1620.7   728.8 1627.78   753.8 1642.64   778.8  1661.9   823.8 1693.78
   873.8 1726.71   888.7 1733.07   913.7    1741   918.7 1741.47   928.7 1740.44
#Mann= 3 , 0 , 0
       0      .1       0   472.5    .045       0   487.5      .1       0
Bank Sta=472.5,487.5
XS Rating Curve= 0 ,0
Exp/Cntr=0.3,0.1

Type RM Length L Ch R = 1 ,944.2   ,246.9,238.1,230.5
XS GIS Cut Line= 4
       1822197.1      217459.154      1821821.36      217363.233
     1821727.818      217353.937     1821259.327      217352.058
#Sta/Elev= 30
       0 1718.46    14.9 1717.35    29.8 1713.84    74.6 1699.37    94.5 1690.03
   149.2  1660.8   203.8  1626.7   253.6 1601.17   293.3 1581.88   333.1 1555.22
   362.9 1538.36   382.8 1523.77   416.3    1510   417.5 1509.68   431.3 1510.88
   516.7 1519.93   546.6 1524.06   596.4 1540.91   611.4 1547.45   671.2 1580.84
   701.1 1596.51   745.9 1625.03   760.9 1633.64   820.7 1676.92   845.6 1696.17
   860.6 1705.19   885.5 1715.55   915.4 1725.04   925.4 1724.52   950.3 1719.24
#Mann= 3 , 0 , 0
       0      .1       0   416.3    .045       0   431.3      .1       0
Bank Sta=416.3,431.3
XS Rating Curve= 0 ,0
Exp/Cntr=0.3,0.1

Type RM Length L Ch R = 1 ,706.2   ,77.1,74.8,72.3
XS GIS Cut Line= 4
     1822234.333      217231.528     1821851.395      217167.108
     1821768.815      217160.666     1821262.028      217298.226
#Sta/Elev= 30
       0 1590.73    54.8  1586.6    69.7 1584.03   104.6  1580.2   139.4  1573.7
   174.2 1563.49   204.1  1557.4   273.8 1538.68   283.8 1534.78   303.7 1523.89
   308.7 1521.99   358.4 1513.43   383.3 1507.34   407.8 1504.56   476.1    1501
   532.3 1499.22   535.6 1499.06   547.3 1500.44   565.3 1504.92   575.2  1508.5
   644.5 1552.43     704 1584.44   723.8    1597   778.3 1625.63   798.1 1638.08
   847.6 1673.82   857.6 1679.83     917 1699.38   971.5 1699.28   996.3 1695.73
#Mann= 3 , 0 , 0
       0      .1       0   532.3    .045       0   547.3      .1       0
Bank Sta=532.3,547.3
XS Rating Curve= 0 ,0
Exp/Cntr=0.3,0.1

Type RM Length L Ch R = 1 ,631.4   ,25.7,25.8,25.8
XS GIS Cut Line= 4
     1822196.682      217147.249     1821858.371      217087.175
      1821756.14      217092.445     1821258.687      217284.259
#Sta/Elev= 30
       0 1543.57    24.9 1541.37    84.7 1528.81   124.5 1523.37   189.2 1509.04
     259 1499.26   273.9 1497.73   308.7 1496.64   348.5 1497.13     407 1495.28
     482 1497.03     497 1497.86   520.7 1499.26   525.7 1500.27   545.6 1508.23
   565.6 1517.66   580.5 1525.56   620.4 1553.63   630.3 1558.94   670.2 1584.25
   695.1 1596.08     715 1607.33   764.9 1630.26   819.7 1657.88   859.5 1675.24
   884.4 1683.56   899.4 1686.86   954.2 1688.74   974.1 1686.64   979.1 1686.85
#Mann= 3 , 0 , 0
       0      .1       0     482    .045       0     497      .1       0
#XS Ineff= 2 , 0
          477.24 1497.15
Permanent Ineff=
       F       F
Bank Sta=482,497
XS Rating Curve= 0 ,0
Exp/Cntr=0.3,0.1

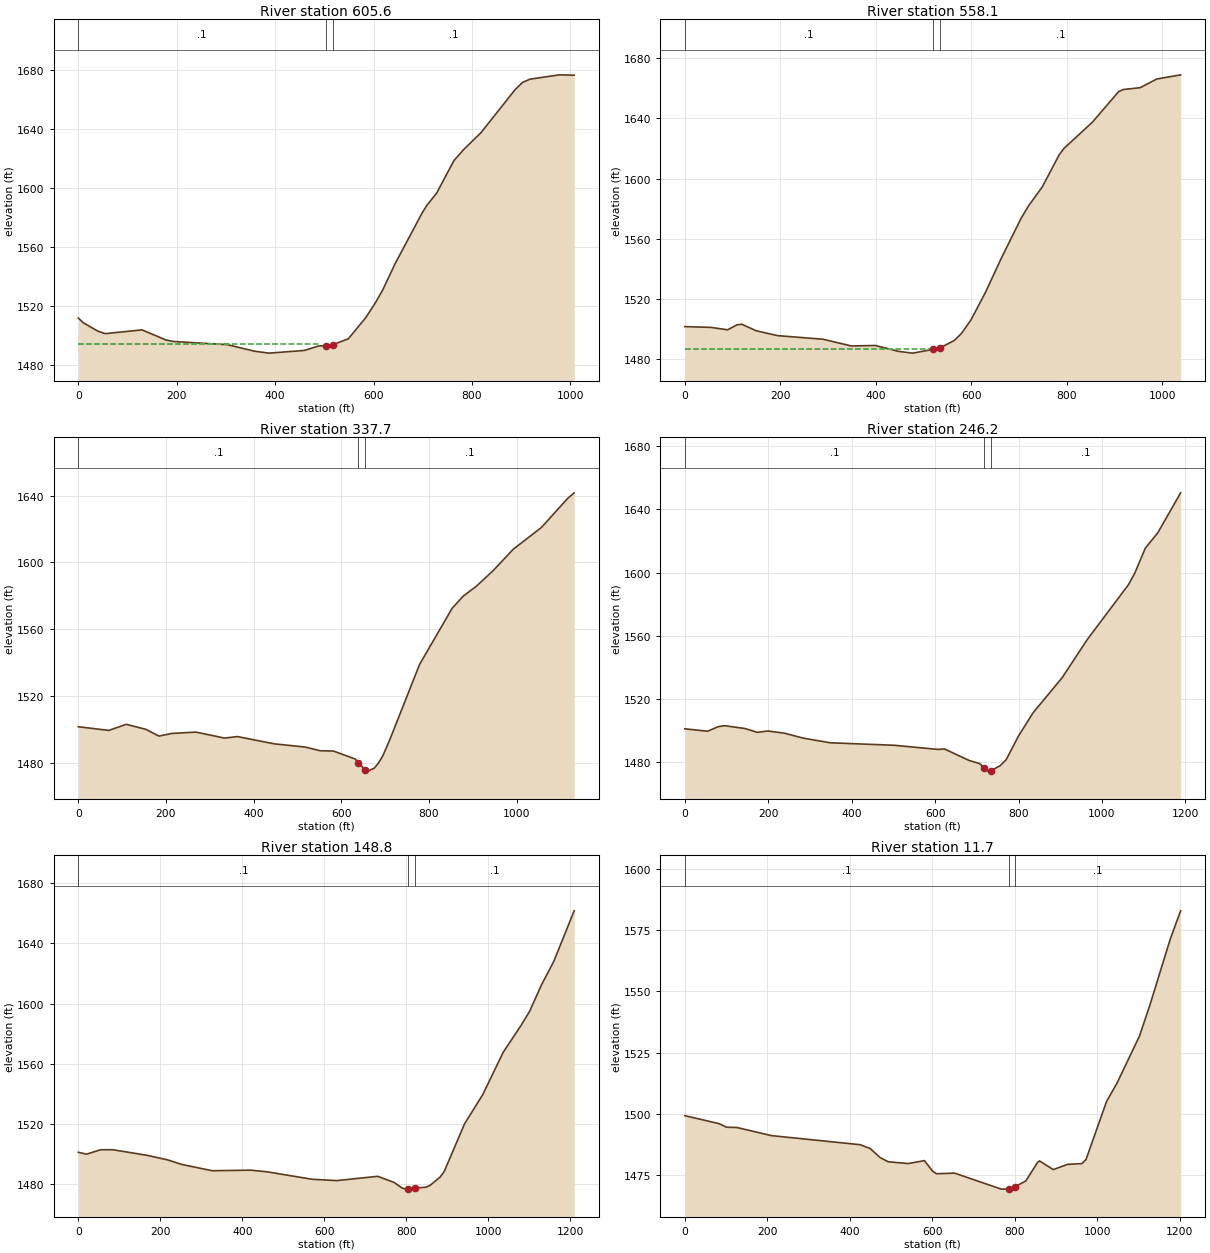
Type RM Length L Ch R = 1 ,605.6   ,65.5,47.5,37.5
XS GIS Cut Line= 4
     1822181.926      217104.038     1821806.729      217006.023
     1821758.637      217065.162     1821253.417      217266.342
#Sta/Elev= 30
       0 1511.96     9.9 1508.83    39.8 1503.05    54.7  1501.4   129.3 1503.95
     179 1496.99   193.9 1496.05   303.3 1493.91     358 1489.49   387.8 1488.18
   459.2 1489.99     489 1493.08     503 1493.23     518    1494   548.8  1497.9
   583.8 1512.06   603.7 1522.28   618.7 1531.05   643.6 1548.67   698.5 1583.13
   708.5 1588.47   728.4  1596.8   763.4  1618.8   783.3 1626.33   818.2 1637.68
   888.1 1667.07     903 1671.88     918 1674.05   977.9    1677  1007.8 1676.76
#Mann= 3 , 0 , 0
       0      .1       0     503    .045       0     518      .1       0
#XS Ineff= 2 , 0
          489.99  1494.2
Permanent Ineff=
       F       F
Bank Sta=503,518
XS Rating Curve= 0 ,0
Exp/Cntr=0.3,0.1

Type RM Length L Ch R = 1 ,558.1   ,199.7,220.4,219
XS GIS Cut Line= 4
     1822172.526      217078.403     1821743.585      216965.465
     1821691.153      217051.612     1821241.082       217254.94
#Sta/Elev= 30
       0 1501.74    54.8 1501.21    89.7 1499.61   109.6 1502.97   119.6 1503.29
   149.5 1498.98   194.4 1495.74   289.1 1493.37   348.9 1488.88   398.7 1489.21
   448.4 1485.25   477.2 1484.13   520.4 1486.63   535.4 1487.74   564.4 1492.56
   579.3 1497.18   599.3 1506.19   629.2 1524.22   664.1 1547.98     704 1573.49
     719  1581.5   748.9 1594.67   783.9 1615.75   793.8 1619.97   853.7 1637.54
   908.6  1657.8   918.6 1659.18   953.5 1660.37   988.4 1666.13  1038.3 1668.91
#Mann= 3 , 0 , 0
       0      .1       0   520.4    .045       0   535.4      .1       0
#XS Ineff= 2 , 0
          516.97  1486.8
Permanent Ineff=
       F       F
Bank Sta=520.4,535.4
XS Rating Curve= 0 ,0
Exp/Cntr=0.3,0.1

Type RM Length L Ch R = 1 ,337.7   ,70,91.4,96.1
XS GIS Cut Line= 4
     1822163.156      217062.785     1821563.444       216864.32
      1821505.39      216936.274     1821206.812      217213.437
#Sta/Elev= 30
       0 1501.66    69.6 1499.46   109.4  1503.1   154.2  1500.1     184 1496.05
   213.9 1497.66   268.6 1498.45   333.3 1494.88   363.1 1495.77   447.7  1491.4
   517.3 1489.52   552.1 1487.29     582 1487.13   631.7 1482.37     639 1480.24
     654 1475.92   660.9  1475.1   675.5 1476.89   685.2 1480.01     695 1484.34
   709.6 1493.13   778.8 1538.97   853.3 1572.62   878.2 1579.76     908 1585.64
   947.7 1595.33   992.4 1607.82    1057 1620.92  1116.6 1638.25  1131.5  1641.6
#Mann= 3 , 0 , 0
       0      .1       0     639    .045       0     654      .1       0
Bank Sta=639,654
XS Rating Curve= 0 ,0
Exp/Cntr=0.3,0.1

Type RM Length L Ch R = 1 ,246.2   ,130,97.5,96.3
XS GIS Cut Line= 4
     1822161.073      217048.208      1821495.75      216810.031
     1821428.544      216867.354     1821112.352      217101.621
#Sta/Elev= 30
       0 1501.09    54.7 1499.55    79.6 1502.39    94.6 1503.09   144.3 1501.26
   174.2 1498.83   199.1 1499.72   238.9  1498.3   283.7  1495.2   348.4 1492.24
   502.6 1490.65   607.1 1488.03   622.1 1488.36   681.8 1481.01   706.7 1479.07
   718.3 1476.28   726.3 1474.34   731.2 1474.29   733.3 1474.52   755.7 1477.69
   770.5 1481.57     800  1496.6   834.8 1511.22   904.6 1533.49   964.4 1557.48
    1064 1592.53  1078.9 1599.82  1103.8 1615.43  1133.7 1625.17  1188.5  1650.5
#Mann= 3 , 0 , 0
       0      .1       0   718.3    .045       0   733.3      .1       0
Bank Sta=718.3,733.3
XS Rating Curve= 0 ,0
Exp/Cntr=0.3,0.1

Type RM Length L Ch R = 1 ,148.8   ,103.8,137.1,170.2
XS GIS Cut Line= 5
     1822148.579       217032.59     1821764.302      216888.021
     1821441.716      216729.102     1821369.605      216794.803
      1821073.15      216964.664
#Sta/Elev= 30
       0 1501.34    19.8 1500.09    54.4 1503.02    84.1 1503.04   168.2  1499.3
   217.6 1496.32   252.3 1493.28   326.5 1489.12   420.6 1489.48   460.5 1488.39
   570.4 1483.45   630.3 1482.56   730.2 1485.41   770.2 1481.35   789.7 1477.64
   799.4 1476.91     805 1477.02     820 1477.48   848.2 1478.22     858 1479.41
   882.6 1484.94   892.5 1488.66     942 1520.18   986.6 1539.65  1036.1 1567.54
  1080.7 1585.82  1100.5  1594.7  1130.2 1612.58  1159.9 1628.06  1209.4 1661.46
#Mann= 3 , 0 , 0
       0      .1       0     805    .045       0     820      .1       0
Bank Sta=805,820
XS Rating Curve= 0 ,0
Exp/Cntr=0.3,0.1

Type RM Length L Ch R = 1 ,11.7    ,8.4,11.7,15
XS GIS Cut Line= 6
     1822139.932      216967.711     1821943.146      216931.269
      1821763.02      216856.303     1821606.841      216776.131
     1821403.808      216620.993     1821046.678      216734.484
#Sta/Elev= 30
       0 1499.28    82.3 1496.06   101.6 1494.56   125.8 1494.46   210.1 1491.13
     425 1487.43   449.4 1485.88   473.7 1482.16   493.2 1480.46     542 1479.73
     581 1480.93   600.6 1476.68   610.4 1475.56   654.4 1475.81   767.5 1469.28
   786.3 1469.31   801.3 1470.32   826.8  1472.6   855.4 1480.18   860.2  1480.8
   893.5 1477.26     928 1479.39   962.9 1479.71   972.8 1481.34  1022.7 1505.07
  1047.7 1512.46  1102.6  1531.8  1127.5  1544.3  1177.4  1571.5  1202.3 1582.93
#Mann= 3 , 0 , 0
       0      .1       0   786.3    .045       0   801.3      .1       0
Bank Sta=786.3,801.3
XS Rating Curve= 0 ,0
Exp/Cntr=0.3,0.1

Chan Stop Cuts=-1
Use User Specified Reach Order=0